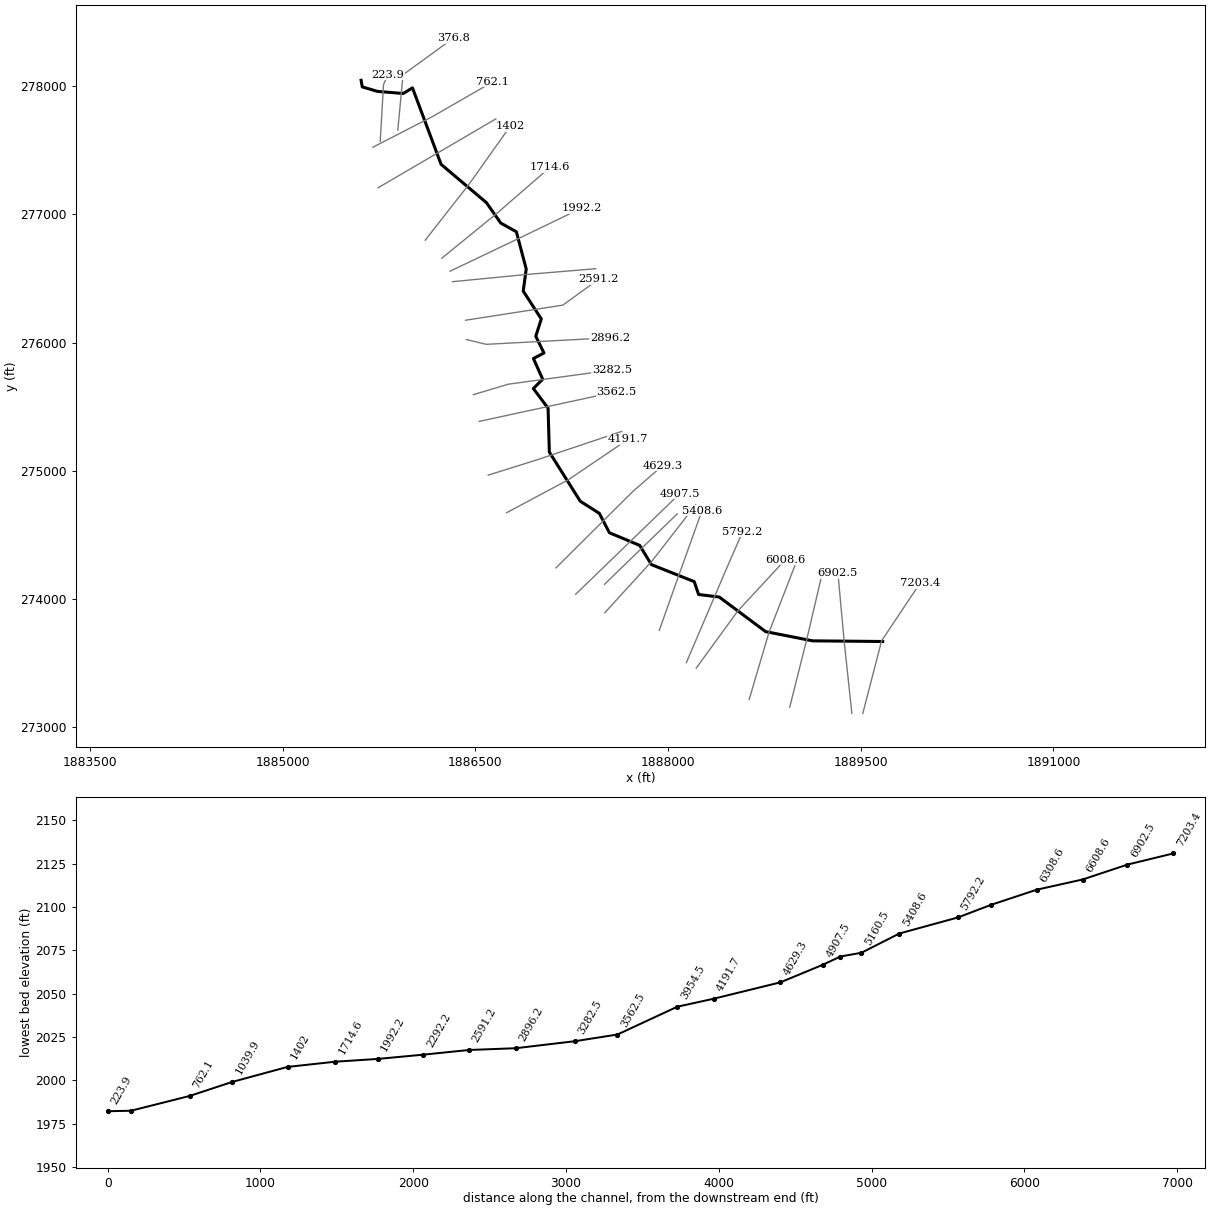
--- LrlBrnch.prj (project) ---

Proj Title=LrlBrnch
Current Plan=p01
Default Exp/Contr=0,0
English Units
Geom File=g01
Flow File=f01
Plan File=p01
BEGIN DESCRIPTION:
END DESCRIPTION:
DSS Export Rating Curves= 0
DSS Export Rating Curve Sorted= 0
DSS Export Volume Flow Curves= 0
DXF OffsetX= 0
DXF OffsetY= 0
DXF ScaleX= 0
DXF ScaleY= 0

--- LrlBrnch.p01 (plan) ---

Plan Title=Floodplain
Program Version=4.00
Geom File=g01
Flow File=f01
K Sum by GR=0
Std Step Tol=0.01
Critical Tol=0.01
Num of Std Step Trials=20
Max Error Tol=0.3
Flow Tol Ratio=0.001
Split Flow NTrial=30
Split Flow Tol=0.02
Split Flow Ratio=0.02
Log Output Level=0
Friction Slope Method=1
Unsteady Friction Slope Method=2
Unsteady Bridges Friction Slope Method=1
Global Log Level=0
CheckData=False
Run HTab=0
Run UNet=0
Run PostProcess=0
UNET Theta=0
UNET Theta Warmup=0
UNET ZTol=0
UNET ZSATol=0
UNET MxIter=0
UNET MaxInSteps=0
UNET DtIC=0
UNET DtMin=0
UNET MaxCRTS=0
UNET WFStab=0
UNET SFStab=0
UNET WFX=0
UNET SFX=0
UNET DSS MLevel=0
UNET DZMax Abort=0
UNET Convert EG Bridges=0
UNET Use Existing IB Tables=0
UNET Froude Limit=0
UNET Froude Power=0
Write IC File=0
Echo Input=False
Echo Output=False
Write Detailed=0

--- LrlBrnch.f01 (steady flow) ---

Flow Title=NFF Regression Equation
Program Version=4.00
Number of Profiles=1
Profile Names=P100yr
River Rch & RM=LrlBrnch,Main      ,7203.4
870.6299
River Rch & RM=LrlBrnch,Main      ,6902.5
873.6521
River Rch & RM=LrlBrnch,Main      ,3954.5
967.8691
River Rch & RM=LrlBrnch,Main      ,223.9
1071.559
Boundary for River Rch & Prof#=LrlBrnch,Main      ,1
Up Type=0
Dn Type=3
Dn Slope=0.011465

--- LrlBrnch.g01 (geometry) ---

Geom Title=USGS 3m DEM
Program Version=4.10

River Reach=LrlBrnch        ,Main
Reach XY= 30
     1889670.334      273667.908      1889124.85      273672.936
     1888759.017      273744.898     1888398.223      274014.533
     1888237.039      274034.691     1888203.397      274134.807
      1887869.77      274267.745     1887778.518      274417.651
     1887542.677      274516.346      1887464.49      274667.592
     1887315.838      274762.219     1887075.086      275145.314
      1887065.22      275488.054     1886950.511      275641.717
     1887023.172      275714.277     1886951.161      275875.896
     1887033.222      275918.878     1886969.401      276049.133
     1887012.389      276184.595     1886871.722      276402.122
     1886895.072      276574.137     1886818.331      276864.523
     1886697.197      276932.258     1886584.779      277092.239
     1886232.206      277390.763      1886009.49      277987.329
      1885937.37      277943.581      1885737.26      277959.984
     1885618.731      277995.156     1885609.349      278046.387

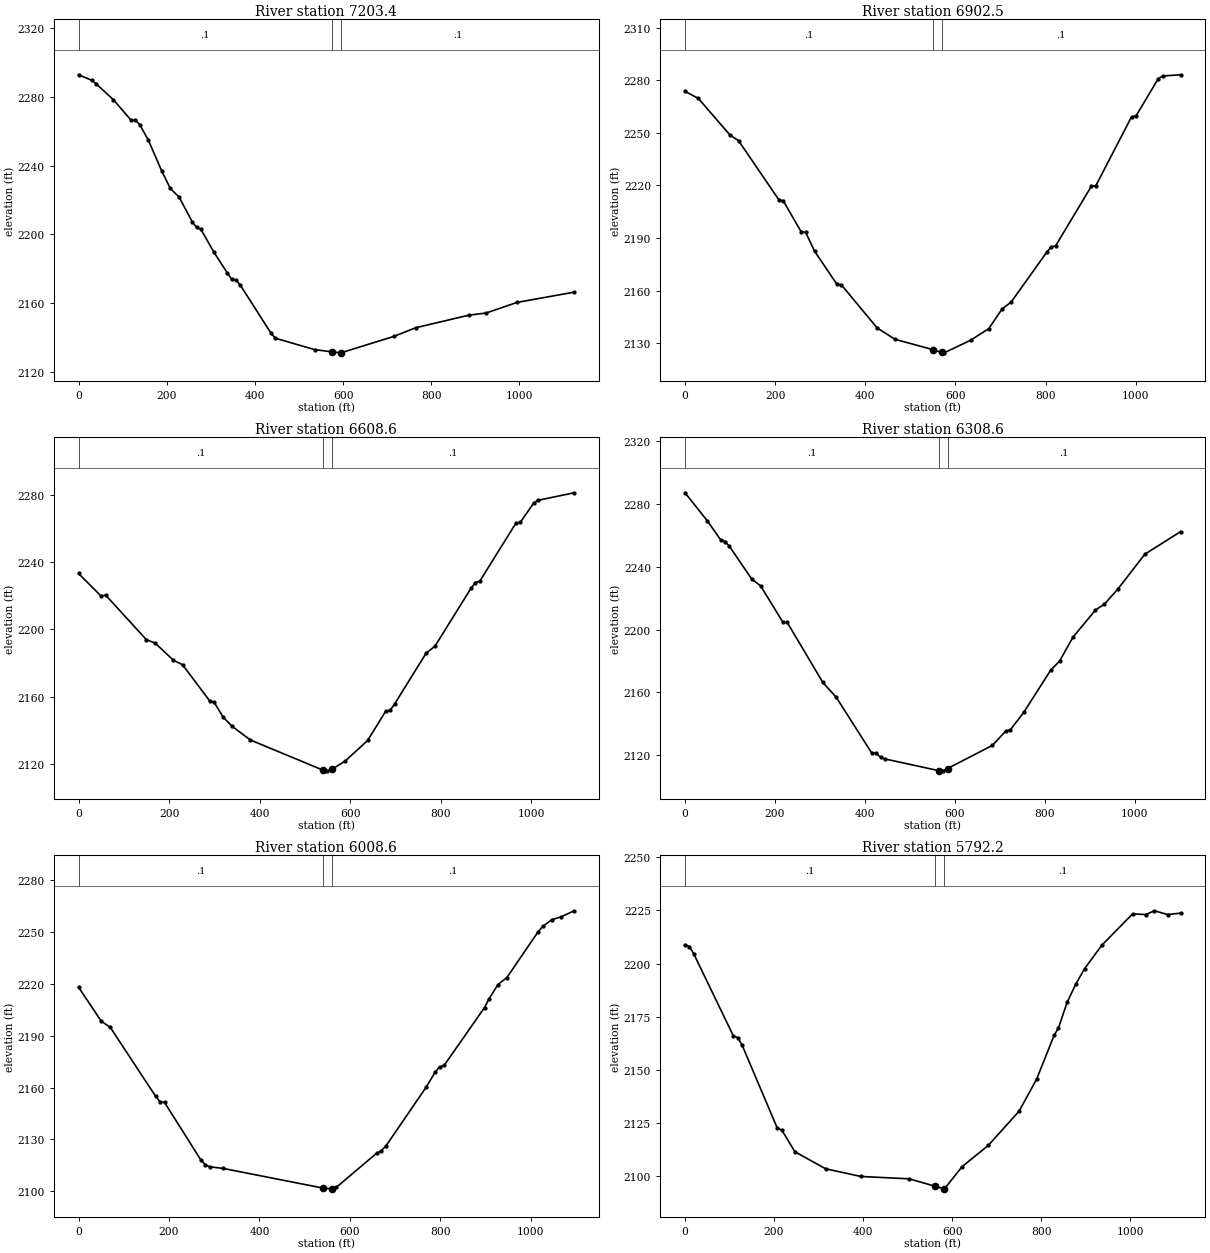
Type RM Length L Ch R = 1 ,7203.4  ,292.2,300.8,317.9
XS GIS Cut Line= 3
     1889515.752      273107.018     1889662.012      273673.452
     1889960.896      274122.132
#Sta/Elev= 30
       0 2292.85    29.8 2289.67    39.7 2287.66    79.3 2278.29     119 2266.47
   128.9 2266.43   138.8 2263.86   158.6 2254.68   188.4 2237.04   208.2 2226.66
   228.1 2221.64   257.8 2207.34   267.7 2203.96   277.6 2202.86   307.4 2189.41
   337.1 2177.62     347 2173.96     357 2173.46   366.9 2170.38   436.3 2142.49
   446.2 2139.48   535.4 2132.83     575 2131.52     595 2130.95   714.8 2140.48
   764.7 2145.56   884.5 2152.84   924.5 2154.15   994.3 2160.29  1124.1 2166.29
#Mann= 3 , 0 , 0
       0      .1       0     575    .045       0     595      .1       0
Bank Sta=575,595
XS Rating Curve= 0 ,0
Exp/Cntr=0.3,0.1

Type RM Length L Ch R = 1 ,6902.5  ,302.6,293.8,285.7
XS GIS Cut Line= 3
     1889430.492      273108.024     1889372.556      273650.063
     1889321.623      274201.937
#Sta/Elev= 30
       0 2273.72    29.7 2269.68    99.1    2249   118.9 2245.54   208.1 2211.87
     218 2211.26   257.7 2193.58   267.6 2193.28   287.4 2182.52     337 2163.66
   346.9 2163.32   426.2 2138.72   465.8 2132.24   549.3 2126.39   569.3 2124.73
   574.8 2124.51   634.2 2131.79   673.8 2138.31   703.5 2149.58   723.3 2153.42
   802.4 2181.92   812.3 2184.91   822.2  2185.6   901.4 2219.57   911.3 2219.88
   990.5 2259.17  1000.4 2259.69  1049.9 2280.99  1059.8 2282.51  1099.4 2283.17
#Mann= 3 , 0 , 0
       0      .1       0   549.3    .045       0   569.3      .1       0
Bank Sta=549.3,569.3
XS Rating Curve= 0 ,0
Exp/Cntr=0.3,0.1

Type RM Length L Ch R = 1 ,6608.6  ,300.9,299.8,296.3
XS GIS Cut Line= 3
     1888946.554      273155.047     1889080.224      273687.843
     1889204.026        274218.8
#Sta/Elev= 30
       0 2233.24    49.9 2219.79    59.9 2220.35   149.8 2193.91   169.8 2191.73
   209.7  2181.6   229.7 2178.99   289.6 2157.51   299.6 2156.63   319.6 2147.74
   339.6  2142.3   379.5 2134.24   539.3 2116.37   549.3  2115.9   559.3 2116.73
     589 2121.75   638.5 2133.96   678.2  2151.3   688.1 2151.91     698 2155.63
   767.4 2185.77   787.2 2190.01   866.5 2224.34   876.4 2227.79   886.3 2228.73
   965.6    2263   975.6 2263.64  1005.3 2275.14  1015.2 2276.74  1094.5 2281.19
#Mann= 3 , 0 , 0
       0      .1       0   539.3    .045       0   559.3      .1       0
Bank Sta=539.3,559.3
XS Rating Curve= 0 ,0
Exp/Cntr=0.3,0.1

Type RM Length L Ch R = 1 ,6308.6  ,308.6,300,290.5
XS GIS Cut Line= 3
     1888631.086      273215.638     1888784.556      273737.386
     1888986.105      274257.906
#Sta/Elev= 30
       0 2287.06    49.4 2269.34    79.1 2257.19      89 2256.03    98.9 2252.92
   148.3  2232.2   168.1 2227.78   217.5 2204.75   227.4 2204.49   306.5  2166.3
   336.2  2156.9   415.3 2121.36   425.2 2121.22   435.1 2118.53     445 2117.58
   563.8 2110.18   573.8 2110.03   583.7  2111.5   683.4 2126.21   713.3  2135.4
   723.3 2136.13   753.2 2147.27     813 2174.09   832.9 2179.93   862.8 2195.18
   912.6  2212.4   932.6 2216.14   962.5 2225.79  1022.3 2247.93    1102 2262.35
#Mann= 3 , 0 , 0
       0      .1       0   563.8    .045       0   583.7      .1       0
Bank Sta=563.8,583.7
XS Rating Curve= 0 ,0
Exp/Cntr=0.3,0.1

Type RM Length L Ch R = 1 ,6008.6  ,210.8,216.4,225
XS GIS Cut Line= 3
     1888218.394      273459.884     1888541.879      273905.289
     1888911.995      274305.698
#Sta/Elev= 30
       0 2218.16      50 2198.53    70.1  2194.9   170.2 2155.03   180.2 2151.73
   190.2 2151.36   270.2  2118.1   280.2 2115.27   290.2 2114.06   320.3 2113.07
   540.5 2101.71   560.4 2101.27   560.5 2101.28   570.3 2102.22   659.5 2122.02
   669.4 2123.39   679.4 2126.06   768.6 2160.23   788.4  2168.9   798.3 2172.01
   808.2 2172.79   897.5 2206.33   907.4 2211.32   927.2 2219.67     947 2223.74
  1016.4 2250.42  1026.4 2253.38  1046.2 2257.27    1066 2258.84  1095.7 2262.43
#Mann= 3 , 0 , 0
       0      .1       0   540.5    .045       0   560.5      .1       0
Bank Sta=540.5,560.5
XS Rating Curve= 0 ,0
Exp/Cntr=0.3,0.1

Type RM Length L Ch R = 1 ,5792.2  ,383,383.3,381.1
XS GIS Cut Line= 3
     1888141.995      273503.045     1888428.148       274175.37
      1888580.31      274526.019
#Sta/Elev= 30
       0  2208.8     9.9 2207.98    19.8 2204.51   108.6 2165.97   118.5 2165.12
   128.4 2161.53   207.4 2122.49   217.2 2121.72   246.8 2111.44     316 2103.43
     395 2099.83   503.6 2098.72   562.1 2095.19   582.1 2094.02   582.6 2094.01
   622.1 2104.42   681.3 2114.49   750.3 2130.57   789.5 2145.58   828.7 2166.17
   838.5 2169.63   858.1 2181.77   877.7 2190.41   897.3 2197.59   936.5 2208.73
  1005.1 2223.34  1034.5 2223.02  1054.1  2224.8  1083.5 2223.04  1112.9 2223.69
#Mann= 3 , 0 , 0
       0      .1       0   562.1    .045       0   582.1      .1       0
Bank Sta=562.1,582.1
XS Rating Curve= 0 ,0
Exp/Cntr=0.3,0.1

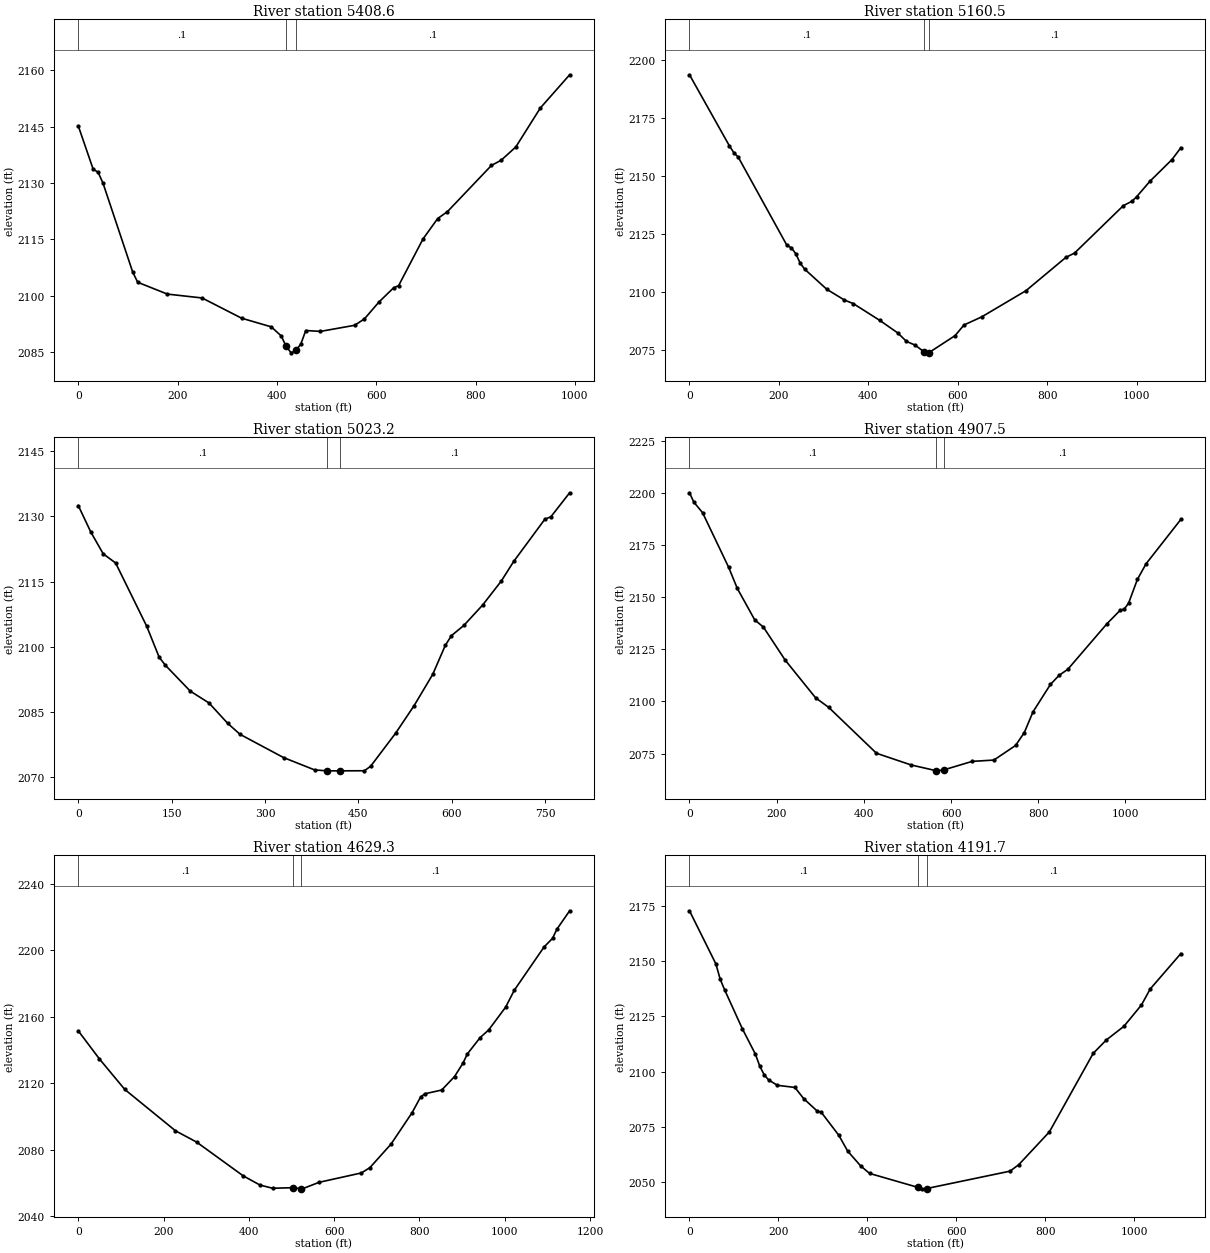
Type RM Length L Ch R = 1 ,5408.6  ,258.2,248.1,238.3
XS GIS Cut Line= 3
     1887931.029      273754.874     1888073.852      274158.922
     1888263.149      274686.932
#Sta/Elev= 30
       0 2145.19    29.9 2133.69    39.9 2132.86    49.8 2129.94   109.6 2106.26
   119.6 2103.55   179.4  2100.4   249.2 2099.37   328.9 2093.98   388.7 2091.67
   408.6 2089.26   418.5  2086.5   428.6 2084.75   438.5 2085.41   448.2 2087.12
   458.1  2090.7   487.6 2090.46   556.5 2092.09   576.2 2093.79   605.7 2098.32
   635.2  2102.1     645 2102.64   694.2 2115.09   723.8 2120.54   743.4 2122.37
     832 2134.68   851.7 2136.07   881.2 2139.62   930.4 2149.97   989.5 2158.83
#Mann= 3 , 0 , 0
       0      .1       0   418.5    .045       0   438.5      .1       0
Bank Sta=418.5,438.5
XS Rating Curve= 0 ,0
Exp/Cntr=0.3,0.1

Type RM Length L Ch R = 1 ,5160.5  ,139,137.2,135.1
XS GIS Cut Line= 3
     1887507.542      273892.681     1887874.082      274295.417
     1888213.668      274733.326
#Sta/Elev= 30
       0 2193.61    89.1 2162.99      99 2160.04   108.9 2158.12   217.8 2120.05
   227.7 2118.97   237.6 2116.44   247.5 2112.36   257.4 2109.78   306.9 2101.09
   346.5 2096.43   366.3  2094.9   425.8 2087.62   465.4 2082.28   485.2  2078.6
     505 2076.94   524.8 2074.01   534.7 2073.66     594  2081.1   613.8 2085.68
   653.4 2089.17   752.4 2100.47   841.4  2114.8   861.2 2116.73   970.1 2137.15
   989.9 2139.12   999.8 2140.99  1029.4 2147.64  1078.9 2157.05  1098.7 2162.14
#Mann= 3 , 0 , 0
       0      .1       0   524.8    .045       0   534.7      .1       0
Bank Sta=524.8,534.7
XS Rating Curve= 0 ,0
Exp/Cntr=0.3,0.1

Type RM Length L Ch R = 1 ,5023.2  ,120.3,115.5,110.8
XS GIS Cut Line= 2
     1887504.224      274113.878     1888070.755      274663.746
#Sta/Elev= 30
       0 2132.49      20 2126.44      40 2121.41      60 2119.29   109.9 2104.76
   129.9 2097.64   139.9 2095.78   179.9 2089.83   209.9 2087.12   239.8 2082.46
   259.8  2079.9   329.8 2074.55   379.8 2071.71   399.8  2071.5   400.4  2071.5
   420.4  2071.5   459.7 2071.52   469.7 2072.55   509.7 2080.12   539.7 2086.52
   569.6 2093.71   589.6 2100.33   599.6 2102.59   619.6 2104.95   649.6 2109.61
   679.6 2115.13   699.6 2119.65   749.5 2129.33   759.5 2129.95   789.5 2135.44
#Mann= 3 , 0 , 0
       0      .1       0   400.4    .045       0   420.4      .1       0
Bank Sta=400.4,420.4
XS Rating Curve= 0 ,0
Exp/Cntr=0.3,0.1

Type RM Length L Ch R = 1 ,4907.5  ,272.3,277.9,283.5
XS GIS Cut Line= 2
     1887280.662      274037.073     1888090.075      274821.301
#Sta/Elev= 30
       0 2199.97      10 2195.46    29.9 2190.47    89.8 2164.27   109.7 2154.12
   149.6 2139.08   169.6  2135.6   219.4 2119.81   289.2 2101.74   319.2 2097.16
   428.9 2075.16   508.6 2069.54   564.6 2066.86   568.5 2066.74   584.6 2067.28
   648.3 2071.27   698.2  2071.9     748 2078.91     768  2085.1   787.9    2095
   827.8 2108.11   847.8 2112.51   867.7 2115.38   957.5 2137.22   987.4 2143.58
   997.4 2144.28  1007.3 2147.16  1027.3 2158.45  1047.2 2165.94    1127  2187.2
#Mann= 3 , 0 , 0
       0      .1       0   564.6    .045       0   584.6      .1       0
Bank Sta=564.6,584.6
XS Rating Curve= 0 ,0
Exp/Cntr=0.3,0.1

Type RM Length L Ch R = 1 ,4629.3  ,445.3,437.6,432.5
XS GIS Cut Line= 3
     1887126.746      274242.587     1887723.584       274836.95
     1887957.193      275040.657
#Sta/Elev= 30
       0 2151.58    49.6 2134.69     109 2116.36   227.9  2091.5   277.5  2084.7
   386.5 2064.44   426.1 2058.86   455.8 2056.94   502.8 2057.28   522.8 2056.68
   525.2 2056.59   564.8 2060.52   663.9 2066.15   683.8 2069.32   733.3 2083.46
   782.8 2102.39   802.7  2111.8   812.6 2113.75   852.3 2116.01   882.3  2124.1
   902.3 2132.23   912.3 2137.67   942.3 2147.52   962.3 2152.11  1002.3 2165.89
  1022.3 2175.96  1092.3 2202.04  1112.3 2207.25  1122.3  2212.7  1152.3  2223.8
#Mann= 3 , 0 , 0
       0      .1       0   502.8    .045       0   522.8      .1       0
Bank Sta=502.8,522.8
XS Rating Curve= 0 ,0
Exp/Cntr=0.3,0.1

Type RM Length L Ch R = 1 ,4191.7  ,241.5,236.7,229.2
XS GIS Cut Line= 3
      1886743.13      274673.151      1887221.99      274929.107
     1887686.486      275244.162
#Sta/Elev= 30
       0 2172.66    59.2 2148.72    69.1 2141.71      79 2136.95   118.5  2119.5
   148.1 2107.93     158 2102.48   167.8 2098.64   177.7  2096.3   197.4 2093.87
   236.9  2092.9   256.7 2087.83   286.3 2082.36   296.2 2081.66   335.7 2071.26
   355.4 2064.17     385  2057.4   404.8 2054.07   513.4 2047.78   523.2 2047.12
     533 2047.26   720.2  2055.1   739.9 2058.01   808.8 2072.84   907.3 2108.31
   936.8 2114.34   976.2 2120.49  1015.6 2130.11  1035.3 2137.34  1104.2 2153.34
#Mann= 3 , 0 , 0
       0      .1       0   513.4    .045       0     533      .1       0
Bank Sta=513.4,533
XS Rating Curve= 0 ,0
Exp/Cntr=0.3,0.1

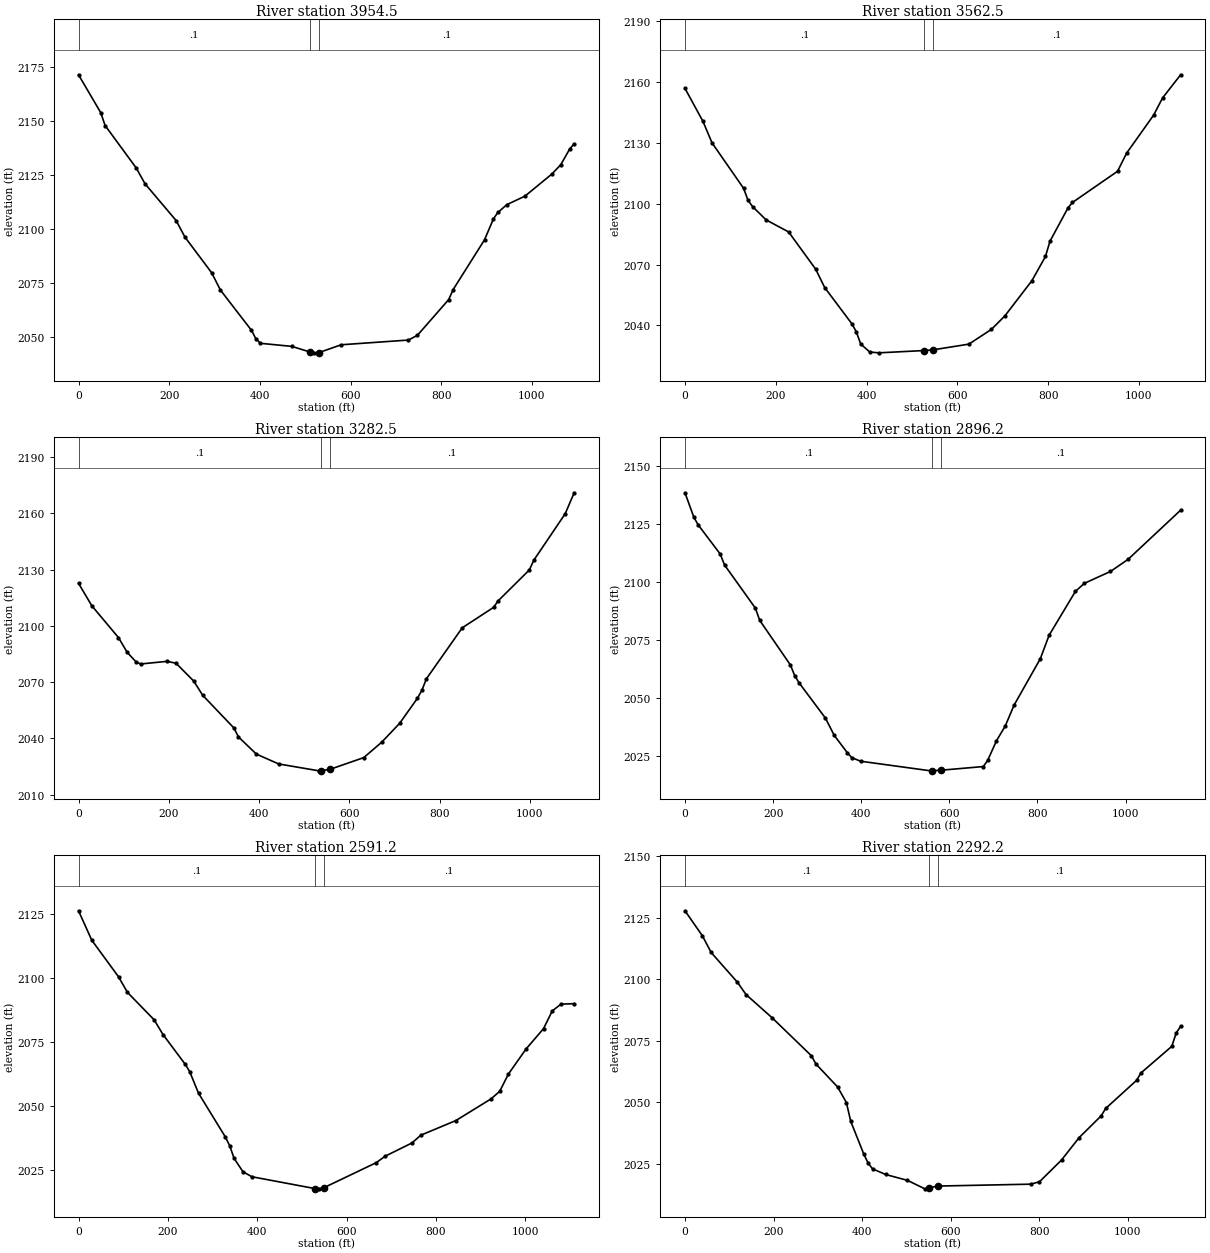
Type RM Length L Ch R = 1 ,3954.5  ,396.6,392.4,388.2
XS GIS Cut Line= 3
       1886598.8      274965.927       1886972.3      275082.877
     1887637.695      275306.775
#Sta/Elev= 30
       0 2171.27    48.9  2153.8    58.7 2147.78   127.2 2128.17   146.8 2120.79
   215.3 2103.81   234.8 2096.12   293.5 2079.68   313.1 2071.61   381.6 2052.96
   391.4 2049.01   401.3 2046.96   470.5 2045.54   509.9 2042.99   519.9 2042.55
   529.9 2042.63   579.3 2046.28   727.6 2048.47   747.4 2050.62   816.6  2067.2
   826.5 2071.87   895.7 2094.89   915.4 2104.63   925.3 2107.57   945.1 2111.18
   984.7 2115.07    1044 2125.28  1063.8 2129.61  1083.6 2136.94  1093.4 2139.28
#Mann= 3 , 0 , 0
       0      .1       0   509.9    .045       0   529.9      .1       0
Bank Sta=509.9,529.9
XS Rating Curve= 0 ,0
Exp/Cntr=0.3,0.1

Type RM Length L Ch R = 1 ,3562.5  ,262.3,279.5,287.1
XS GIS Cut Line= 3
     1886528.881      275385.122     1887062.592      275500.892
     1887596.038      275617.008
#Sta/Elev= 30
       0 2156.84    39.7 2140.56    59.6 2129.99   129.1 2107.61     139 2101.63
   148.9  2098.6   178.7 2092.04   228.4 2086.08     288 2067.74   307.8  2058.7
   367.4 2040.91   377.3 2036.97   387.2 2030.85   407.1 2026.91     427  2026.5
   526.7 2027.63   546.7 2027.98   625.5 2030.79   675.2 2038.07   704.9 2044.72
   764.5  2062.1   794.3 2074.01   804.2 2081.51   843.9 2097.96   853.8 2100.63
   953.1 2115.99     973  2124.9  1032.5 2143.64  1052.4 2152.18  1092.1 2163.56
#Mann= 3 , 0 , 0
       0      .1       0   526.7    .045       0   546.7      .1       0
Bank Sta=526.7,546.7
XS Rating Curve= 0 ,0
Exp/Cntr=0.3,0.1

Type RM Length L Ch R = 1 ,3282.5  ,407.3,386.1,369.8
XS GIS Cut Line= 3
     1886483.507      275593.874     1886756.433       275675.47
     1887562.113      275785.863
#Sta/Elev= 30
       0 2122.74    29.5 2110.72    88.4 2093.79     108 2085.84   127.7 2080.74
   137.5 2079.66   196.5 2081.08   216.1 2080.05   255.4 2070.51     275 2062.99
   344.4 2045.47   354.3 2040.77     394 2031.58   443.5 2026.31   532.8 2022.64
   536.8  2022.7   556.8 2023.41     632 2029.71   671.6  2037.9   711.3 2047.95
     751 2061.41   760.9 2065.72   770.8 2071.79   850.1 2098.96   919.6 2109.88
   929.5 2113.32   998.9 2129.88  1008.8 2135.08  1078.2 2159.84  1098.1 2171.03
#Mann= 3 , 0 , 0
       0      .1       0   536.8    .045       0   556.8      .1       0
Bank Sta=536.8,556.8
XS Rating Curve= 0 ,0
Exp/Cntr=0.3,0.1

Type RM Length L Ch R = 1 ,2896.2  ,288,305.1,321.1
XS GIS Cut Line= 3
     1886428.574        276023.9     1886583.825      275986.507
     1887547.697      276037.776
#Sta/Elev= 30
       0 2138.52      20 2128.04    29.9 2124.69    79.8 2112.16    89.8 2107.38
   159.7  2088.8   169.6 2083.51   239.3 2064.26   249.2 2059.57   259.2 2056.51
   318.9 2041.31   338.8 2033.88   368.7 2026.37   378.6  2024.3   398.5 2022.76
   557.7 2018.61   560.5 2018.64   580.5 2018.87   677.1 2020.46   687.1 2023.17
     707  2031.6   726.9 2037.95   746.8 2046.91   806.5 2066.97   826.4 2077.09
   886.1 2095.99     906 2099.43   965.7  2104.6  1005.5 2109.79  1124.9 2131.02
#Mann= 3 , 0 , 0
       0      .1       0   560.5    .045       0   580.5      .1       0
Bank Sta=560.5,580.5
XS Rating Curve= 0 ,0
Exp/Cntr=0.3,0.1

Type RM Length L Ch R = 1 ,2591.2  ,299.6,298.6,297.3
XS GIS Cut Line= 3
      1886423.18      276174.496     1887180.263      276292.416
     1887458.184      276493.961
#Sta/Elev= 30
       0 2126.27    29.8 2114.74    89.6 2100.46   109.5 2094.39   169.2 2083.67
   189.1 2077.91   238.8 2066.28   248.8 2063.42   268.7 2054.94   328.4 2037.95
   338.3  2034.5   348.3 2029.49   368.2 2024.25   388.1 2022.32   529.8 2017.67
   537.3 2017.59   549.8 2018.08   666.7 2027.84   686.6 2030.37   746.3 2035.51
   766.2 2038.55   844.7 2044.28   923.2 2052.72   942.8 2055.69   962.4 2062.48
  1001.6 2072.21  1040.9  2080.2  1060.5 2087.14  1080.1 2089.78  1109.5 2089.96
#Mann= 3 , 0 , 0
       0      .1       0   529.8    .045       0   549.8      .1       0
Bank Sta=529.8,549.8
XS Rating Curve= 0 ,0
Exp/Cntr=0.3,0.1

Type RM Length L Ch R = 1 ,2292.2  ,290.9,300,309.4
XS GIS Cut Line= 3
     1886321.292      276475.267     1886880.035      276529.853
     1887435.782      276576.469
#Sta/Elev= 30
       0  2127.9    39.4 2117.71    59.1 2110.95   118.2 2098.91   137.9 2093.85
     197 2084.38   285.6 2068.96   295.5 2065.67   344.7 2056.28   364.4 2049.98
   374.3 2042.32   403.8 2028.99   413.7 2025.31   423.5 2023.03   453.1 2020.74
   502.3 2018.35   541.7 2014.91   551.4 2015.34   571.4 2016.04   780.5 2016.81
   800.4 2017.78   850.2 2026.63     890 2035.74   939.8 2044.59   949.8 2047.56
  1019.5 2058.98  1029.5    2062  1099.2 2072.82  1109.1 2078.26  1119.1 2080.94
#Mann= 3 , 0 , 0
       0      .1       0   551.4    .045       0   571.4      .1       0
Bank Sta=551.4,571.4
XS Rating Curve= 0 ,0
Exp/Cntr=0.3,0.1

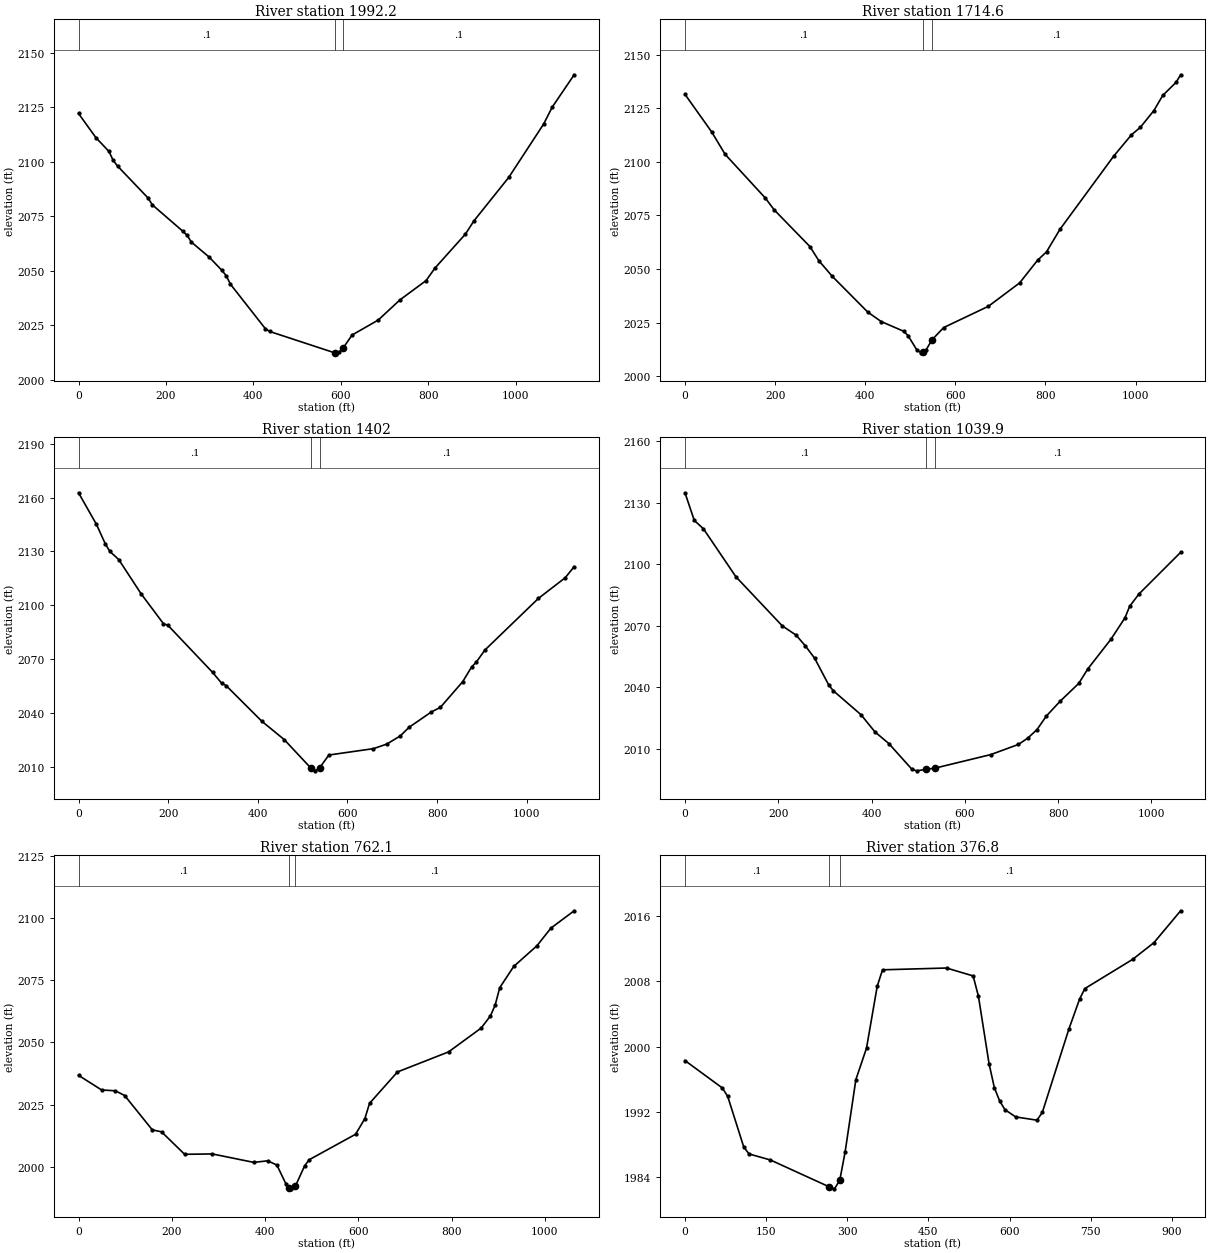
Type RM Length L Ch R = 1 ,1992.2  ,271.6,277.5,283.9
XS GIS Cut Line= 3
     1886301.828       276556.83     1886839.554      276814.106
     1887323.831      277048.274
#Sta/Elev= 30
       0 2122.24    39.7 2111.18    69.6 2104.84    79.5 2100.68    89.4  2098.1
     159 2083.49   168.9 2080.33   238.4 2068.27   248.4 2066.37   258.3 2063.22
     298 2056.52   327.9 2050.32   337.8 2047.84   347.7  2043.9   427.2 2023.58
   437.1 2022.25   586.1 2012.43   596.1 2012.64   606.1 2014.84     626 2020.62
   685.8 2027.48   735.6 2036.76   795.3 2045.59   815.3 2051.27     885 2066.86
   904.9 2073.03   984.6 2092.99  1064.3 2117.45  1084.2  2125.3    1134    2140
#Mann= 3 , 0 , 0
       0      .1       0   586.1    .045       0   606.1      .1       0
Bank Sta=586.1,606.1
XS Rating Curve= 0 ,0
Exp/Cntr=0.3,0.1

Type RM Length L Ch R = 1 ,1714.6  ,306.4,312.1,317.2
XS GIS Cut Line= 3
     1886237.508      276658.202     1886659.391       277002.39
     1887078.981      277366.659
#Sta/Elev= 30
       0  2131.6    59.4    2114    89.1 2103.58   178.2 2083.19     198 2077.63
   277.2 2060.51     297 2053.92   326.7 2046.62   405.9 2029.83   435.6 2025.44
   485.1 2020.94     495  2018.9   514.8 2012.11   524.7 2010.83   528.4 2011.28
   534.6 2012.03   548.4 2016.95   574.2 2022.64   673.5 2032.58   742.9 2043.53
   782.6 2054.11   802.4 2057.99   832.2 2068.52   951.3 2102.67     991  2112.7
  1010.8 2116.21  1040.6 2123.98  1060.4 2131.08  1090.2 2137.27  1100.1 2140.74
#Mann= 3 , 0 , 0
       0      .1       0   528.4    .045       0   548.4      .1       0
Bank Sta=528.4,548.4
XS Rating Curve= 0 ,0
Exp/Cntr=0.3,0.1

Type RM Length L Ch R = 1 ,1402    ,371.7,362.6,353.5
XS GIS Cut Line= 3
     1886108.824      276799.225     1886452.717      277239.463
     1886768.871      277686.176
#Sta/Elev= 30
       0 2162.65    39.9 2145.12    59.8  2134.2    69.8 2130.05    89.8 2125.46
   139.7 2106.39   189.5 2089.77   199.5 2088.85   299.3 2062.61   319.2 2056.64
   329.2 2055.32     409 2035.44   458.9 2025.25     518 2009.49   528.7 2007.83
     538 2009.51   558.6 2016.64   658.1 2020.19     688 2022.74   717.8 2027.26
   737.7  2032.1   787.5 2040.66   807.4 2043.17   857.2 2057.47     877 2065.63
     887 2068.22   906.9 2075.13  1026.3 2103.88    1086 2115.35  1105.9 2121.52
#Mann= 3 , 0 , 0
       0      .1       0     518    .045       0     538      .1       0
Bank Sta=518,538
XS Rating Curve= 0 ,0
Exp/Cntr=0.3,0.1

Type RM Length L Ch R = 1 ,1039.9  ,279,277.2,275.3
XS GIS Cut Line= 2
     1885741.893      277207.981     1886658.487      277745.273
#Sta/Elev= 30
       0 2134.77    19.9 2121.32    39.7 2117.16   109.2  2093.8   208.5 2069.88
   238.3 2065.33   258.2 2060.06     278 2054.06   307.8 2041.17   317.8 2038.25
   377.3 2026.54   407.1 2018.19   436.9 2012.47   486.6  1999.9   496.5 1999.16
   515.7 1999.85   535.7 2000.46   655.4 2007.08   714.9 2012.04   734.8 2015.12
   754.6 2019.26   774.5 2025.85   804.3 2033.13     844 2041.77   863.9 2048.99
   913.5 2063.47   943.3 2073.82   953.2 2079.39   973.1 2085.39  1062.5 2105.71
#Mann= 3 , 0 , 0
       0      .1       0   515.7    .045       0   535.7      .1       0
Bank Sta=515.7,535.7
XS Rating Curve= 0 ,0
Exp/Cntr=0.3,0.1

Type RM Length L Ch R = 1 ,762.1   ,324.7,384.9,412.2
XS GIS Cut Line= 3
     1885701.985        277524.6     1886167.828      277764.973
     1886634.278      278034.062
#Sta/Elev= 30
       0 2036.77    49.4 2030.89    79.1 2030.54    98.9 2028.65   158.2 2014.83
     178 2014.04   227.5    2005   286.8 2005.15   375.8 2001.75   405.5 2002.38
   425.3 2000.68   445.1 1992.95   452.2 1991.63     455 1991.11   464.9 1992.16
   484.6 2000.28   494.5 2002.81     594 2013.06     614 2019.37   623.9 2025.48
   683.8 2038.12   793.4 2046.19   863.3 2055.78   883.2 2060.66   893.2 2064.99
   903.2 2072.04   933.1 2080.56   982.9 2088.88  1012.8 2095.97  1062.7 2102.95
#Mann= 3 , 0 , 0
       0      .1       0   452.2    .045       0   464.9      .1       0
Bank Sta=452.2,464.9
XS Rating Curve= 0 ,0
Exp/Cntr=0.3,0.1

Type RM Length L Ch R = 1 ,376.8   ,151.8,152.9,154.1
XS GIS Cut Line= 3
     1885895.101      277657.901     1885936.117      278090.276
     1886325.767      278373.969
#Sta/Elev= 30
       0 1998.29    69.1 1994.93      79 1993.89   108.6  1987.7   118.4 1986.84
   157.9  1986.1   266.5 1982.81   276.4 1982.56   286.2 1983.62   296.1  1987.1
   315.9 1995.95   335.6 1999.82   355.4 2007.41   365.2 2009.42   483.5 2009.64
   532.7 2008.67   542.5 2006.18   562.2 1997.88     572 1994.95   581.9 1993.31
   591.7 1992.26   611.4 1991.38   650.7 1990.98   660.6 1991.93   709.7 2002.15
   729.4 2005.81   739.2 2007.12   827.8 2010.71   867.1 2012.76   916.3 2016.66
#Mann= 3 , 0 , 0
       0      .1       0   266.5    .045       0   286.2      .1       0
Bank Sta=266.5,286.2
XS Rating Curve= 0 ,0
Exp/Cntr=0.3,0.1

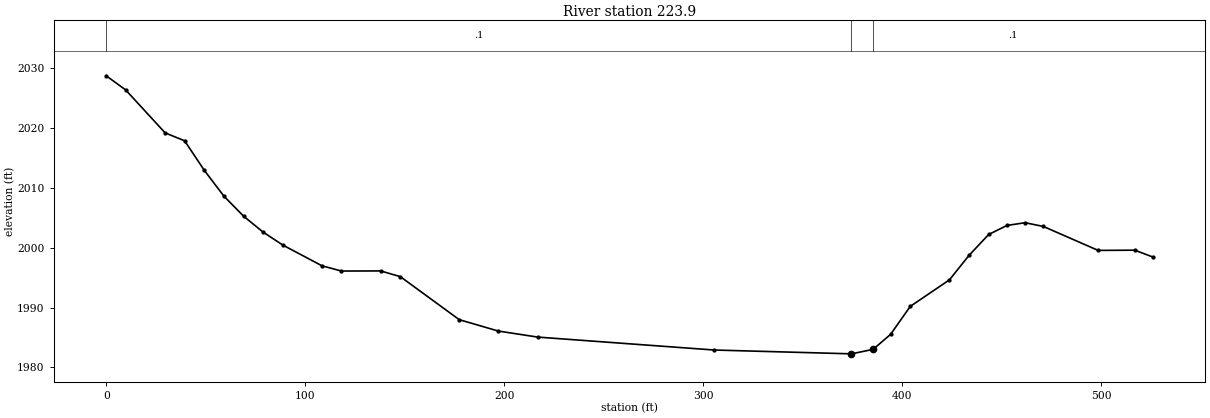
Type RM Length L Ch R = 1 ,223.9   ,261.1,223.9,180.1
XS GIS Cut Line= 3
     1885758.382      277570.743     1885784.017      278013.372
     1885818.196      278088.567
#Sta/Elev= 30
       0 2028.75     9.8 2026.38    29.6 2019.21    39.4 2017.88    49.3 2012.94
    59.1 2008.65      69 2005.29    78.8 2002.63    88.7 2000.46   108.4 1996.99
   118.2 1996.11   137.9 1996.13   147.8 1995.17   177.4 1987.98     197 1986.08
   216.8 1985.07   305.4 1982.91   374.4 1982.27   385.3 1983.01   394.1 1985.52
     404  1990.2   423.7 1994.64   433.5 1998.72   443.4 2002.22   452.6 2003.73
   461.7 2004.19   470.9 2003.56   498.4 1999.56   516.8  1999.6     526 1998.44
#Mann= 3 , 0 , 0
       0      .1       0   374.4    .045       0   385.3      .1       0
Bank Sta=374.4,385.3
XS Rating Curve= 0 ,0
Exp/Cntr=0.3,0.1

Chan Stop Cuts=-1
Use User Specified Reach Order=0
Composite Channel Slope=5